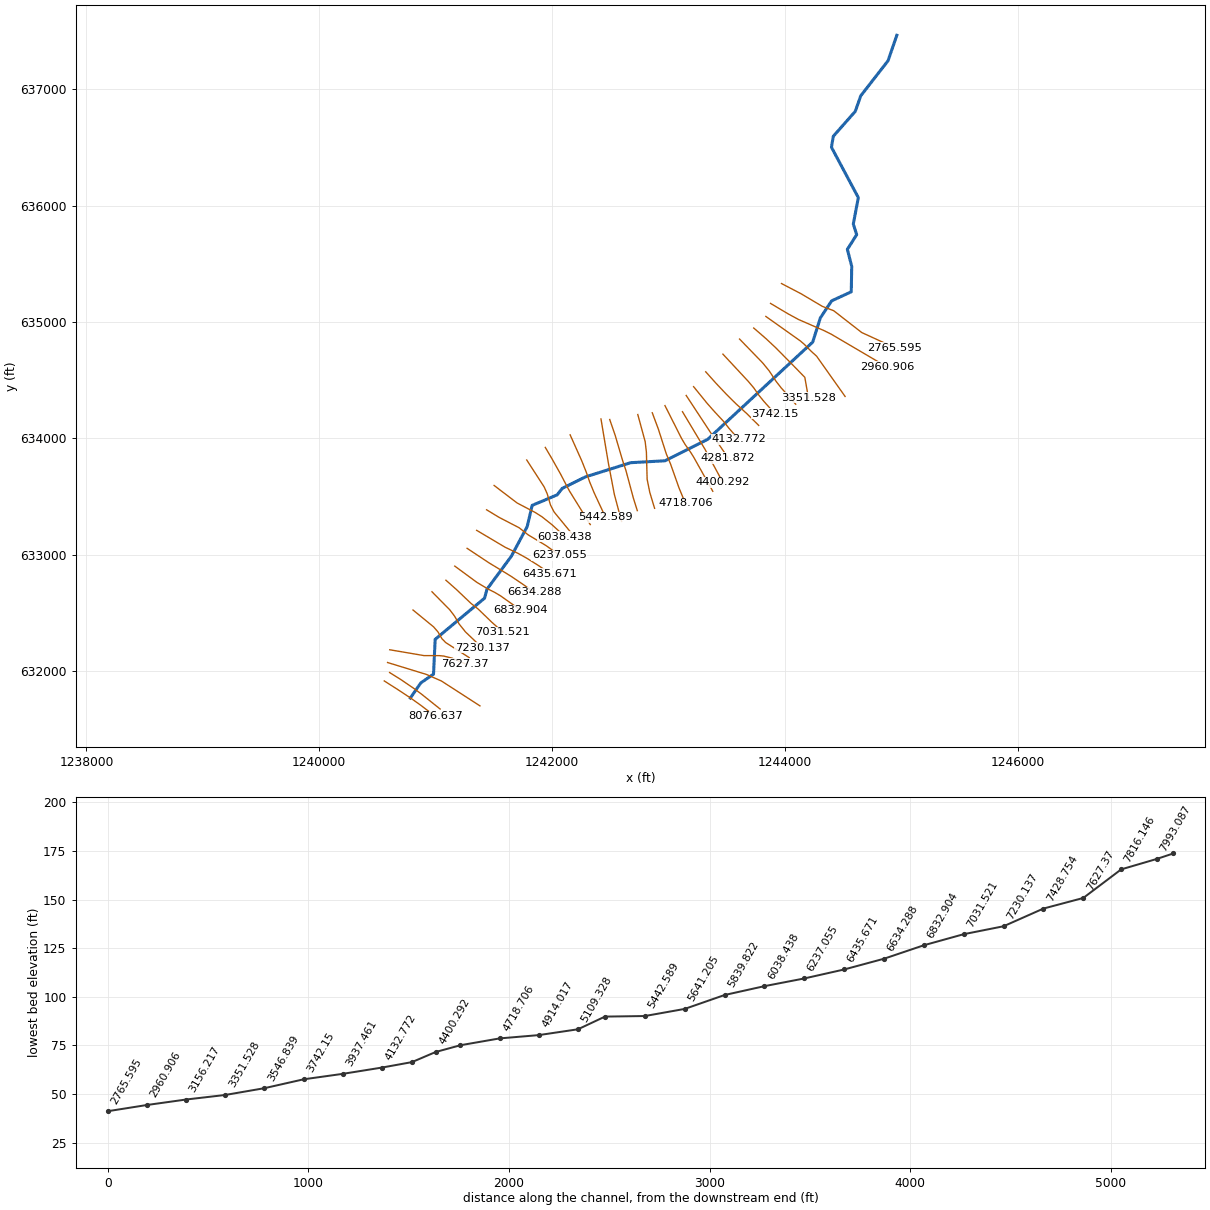
--- 712_ras.prj (project) ---

Proj Title=712
Current Plan=p01
Default Exp/Contr=0.3,0.1
English Units
Geom File=g01
Flow File=f01
Plan File=p01
Y Axis Title=Elevation
X Axis Title(PF)=Main Channel Distance
X Axis Title(XS)=Station
BEGIN DESCRIPTION:
RFD model 712 exported to HEC-RAS
END DESCRIPTION:

--- 712_ras.p01 (plan) ---

Plan Title=Plan 01
Program Version=4.10
Short Identifier=Plan 01
Geom File=g01
Flow File=f01
Subcritical Flow
Calc Critical at every XS
Secant Critical Depth

--- 712_ras.f01 (steady flow) ---

Flow Title=Flow 01
Program Version=5.01
Number of Profiles= 5
Profile Names=10yr,25yr,50yr,100yr,500yr
River Rch & RM=712,43,8076.637
  475.62  585.44  702.92  773.91  945.18
River Rch & RM=712,43,7816.146
  479.42  590.79  709.54  782.12  956.65
River Rch & RM=712,43, 7627.37
  514.53  640.64  771.21  859.03  1064.9
River Rch & RM=712,43,7428.754
  558.44  703.69  849.42  957.68 1205.78
River Rch & RM=712,43,7230.137
  565.35  713.67  861.82  973.42 1228.46
River Rch & RM=712,43,7031.521
  575.46  728.33  880.04  996.61 1261.96
River Rch & RM=712,43,6832.904
  591.29  751.33  908.65 1033.15 1314.98
River Rch & RM=712,43,6634.288
  625.33  801.12  970.66 1112.84 1431.53
River Rch & RM=712,43,6435.671
  629.91  807.84  979.05 1123.66 1447.46
River Rch & RM=712,43,6237.055
  634.85   815.1   988.1 1135.36  1464.7
River Rch & RM=712,43,6038.438
  647.33   833.5 1011.06 1165.09 1508.62
River Rch & RM=712,43,5839.822
  650.89  838.75 1017.61  1173.6 1521.21
River Rch & RM=712,43,5641.205
  657.14  847.99 1029.15 1188.58 1543.42
River Rch & RM=712,43,5442.589
  660.23  852.56 1034.86 1196.01 1554.45
River Rch & RM=712,43,5243.972
  696.07  905.82 1101.43 1282.94 1684.24
River Rch & RM=712,43,4914.017
  700.31  912.15 1109.35 1293.32 1699.83
River Rch & RM=712,43,4718.706
  704.86  918.94 1117.85 1304.49 1716.62
River Rch & RM=712,43,4523.395
  715.53  934.91 1137.84 1330.77  1756.2
River Rch & RM=712,43,4281.872
   724.3  948.05  1154.3 1352.45 1788.94
River Rch & RM=712,43,4132.772
  725.97  950.55 1157.43 1356.58 1795.19
River Rch & RM=712,43,3937.461
  730.28  957.02 1165.54 1367.28 1811.38
River Rch & RM=712,43, 3742.15
   739.1  970.28 1182.17 1389.25 1844.69
River Rch & RM=712,43,3546.839
  741.36  973.69 1186.43  1394.9 1853.26
River Rch & RM=712,43,3351.528
  745.22  979.49 1193.71 1404.53 1867.89
River Rch & RM=712,43,3156.217
  749.99  986.68 1202.73 1416.48 1886.07
River Rch & RM=712,43,2960.906
  756.91  997.12 1215.83 1433.85 1912.52
River Rch & RM=712,43,2765.595
  761.26  1003.7 1224.08  1444.8 1929.23
River Rch & RM=712,43,2570.283
  773.79 1022.66 1247.88 1476.45 1977.61
River Rch & RM=712,43,2374.972
  793.04 1051.87 1284.57 1525.41 2052.73
River Rch & RM=712,43,2179.661
   794.5 1054.08 1287.35 1529.11 2058.43
River Rch & RM=712,43, 1984.35
  796.81  1057.6 1291.77 1535.03 2067.53
River Rch & RM=712,43,1789.039
  803.41 1067.64 1304.39 1551.92 2093.55
River Rch & RM=712,43,1593.728
  808.79 1075.85 1314.71 1565.74 2114.88
River Rch & RM=712,43,1321.084
   810.2    1078 1317.41 1569.36 2120.47
River Rch & RM=712,43,1007.794
  890.62  1201.5 1472.97 1779.41 2447.84
River Rch & RM=712,43,812.4833
  945.88 1287.33 1581.33 1927.41 2681.88
River Rch & RM=712,43,617.1722
  982.72 1344.95 1654.21 2027.66  2841.9
River Rch & RM=712,43, 421.861
   987.3 1352.14 1663.32 2040.23 2862.05
River Rch & RM=712,43,226.5499
  991.03    1358 1670.73 2050.46 2878.46
River Rch & RM=712,43, 31.2388
   993.3 1361.56 1675.24  2056.7 2888.46
Boundary for River Rch & Prof#=712,43,1
Up Type= 0
Dn Type= 2
Boundary for River Rch & Prof#=712,43,2
Up Type= 0
Dn Type= 2
Boundary for River Rch & Prof#=712,43,2
Up Type= 0
Dn Type= 2
Boundary for River Rch & Prof#=712,43,2
Up Type= 0
Dn Type= 2
Boundary for River Rch & Prof#=712,43,2
Up Type= 0
Dn Type= 2

--- 712_ras.g01 (geometry) ---

Geom Title=712
Program Version=4.10

River Reach=712,43
Reach XY= 30
1240782.94063744631769.0301997211240873.01220527631899.067893326
1240982.10725135631974.030133098 1240996.2739225632273.196710557
1241420.44047442632626.5299266431241441.27380377632703.196569964
1241650.44041702632986.5298130961241787.10705084633242.363066539
1241829.60704359633424.0296780321242043.77364969633514.029645085
1242087.94030496633569.8629605921242287.94024885633669.029591963
1242675.44013807633790.696211219 1242971.2733846633807.362864345
1243337.93994847633991.5294657051244240.08218715634826.854837924
1244305.43969348 635034.029128091244402.93966904635181.529081464
1244571.27295497635259.0290535691244575.43962672635477.362321988
 1244537.9396421635624.0289461761244617.93962216635749.862239838
1244588.77296677635841.5288801341244632.10629392636068.195478275
1244401.07597041636501.1901841161244417.17534876636595.486542895
1244605.76806632 636809.378283531244652.93964663636943.195217997
  1244887.106253637244.0284552131244962.93957034637463.195054606

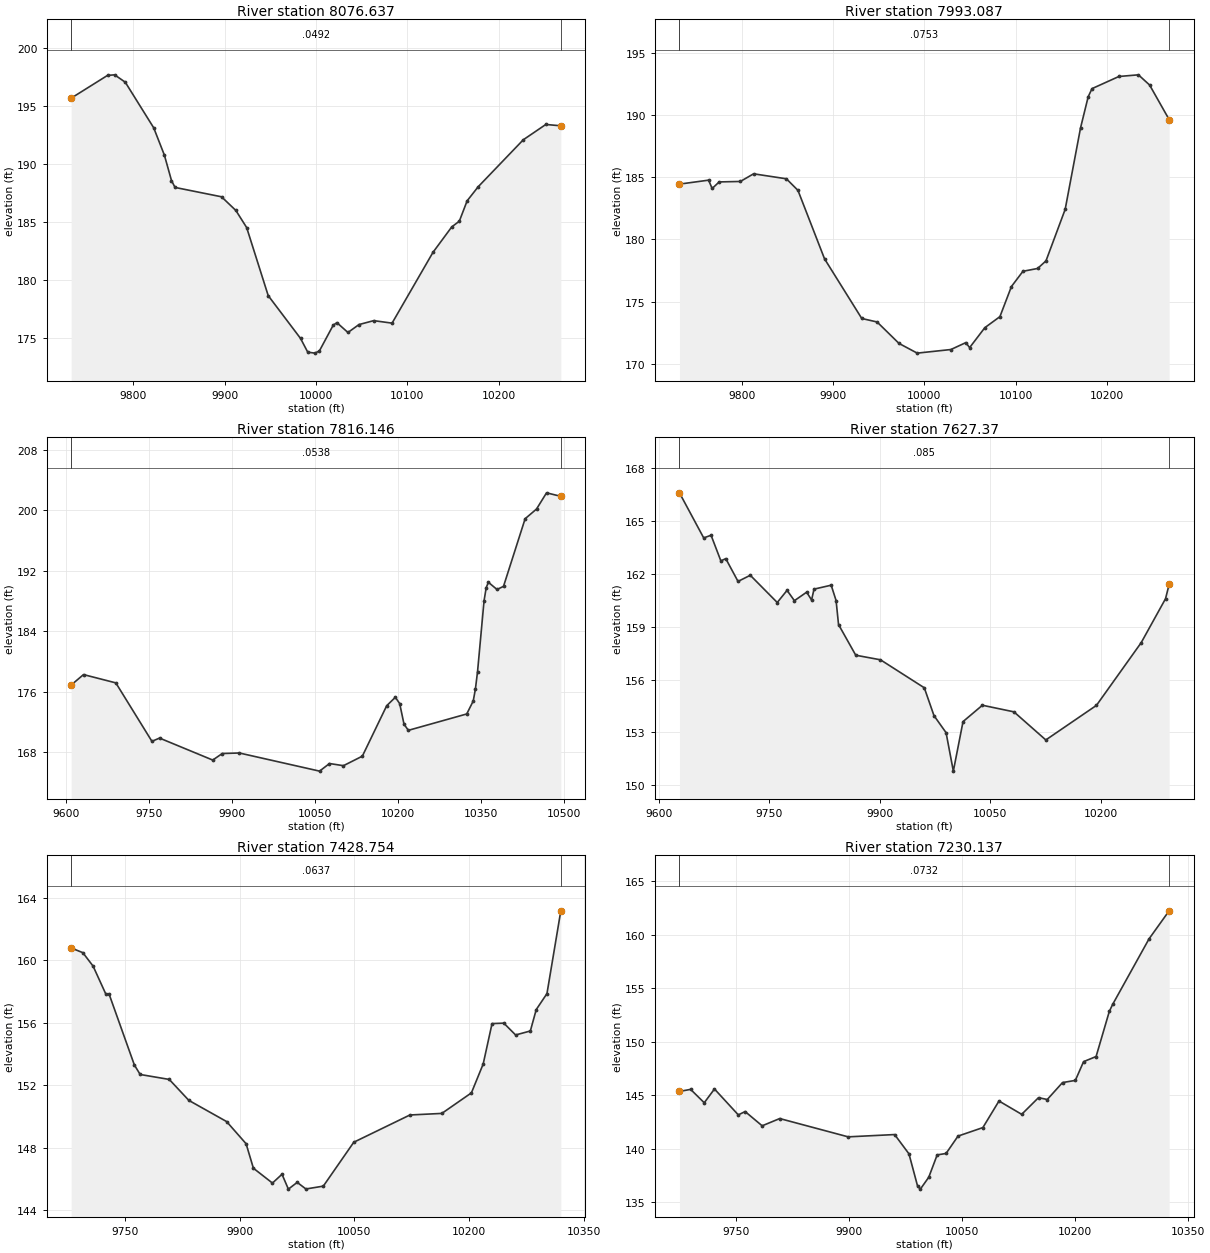
Type RM Length L Ch R = 1 ,8076.637,83.550000,83.550000,83.550000
XS GIS Cut Line= 6
1240558.70048643631915.7069724041240676.59464911631840.570251615
 1240782.6859313631770.4212873471240790.32571627631765.137341772
1240870.04971329631708.4519126231240999.03013449631610.635130836
#Sta/Elev= 30
9732.012195.65079771.818197.60879779.599197.65829791.271197.02159822.395193.0967
9834.066190.74939841.847188.55989845.738187.96959896.583187.16579912.316185.9873
9924.115184.51859947.714178.66059983.113 174.9789990.979173.79839998.845173.7144
10003.71   173.910018.88176.121410022.91176.336510034.99175.490210047.06176.1714
10063.17 176.50910083.29176.294510128.07182.386410148.65184.577610156.89185.0632
10165.45186.818210177.48188.022910226.89 192.06910251.59 193.38810267.99193.2719
#Mann= 3 , 0 , 0
9732.012  0.0492       09732.012  0.0492       010267.99  0.0492       0
#XS Ineff= 2 , 0
       0                               0
Bank Sta=9732.012,10267.99
Exp/Cntr=0.3,0.1

Type RM Length L Ch R = 1 ,7993.087,176.940800,176.940800,176.940800
XS GIS Cut Line= 6
 1240604.5640307631987.818006087 1240700.5449754631928.013948568
1240815.93585076631849.2875882311240827.34134317631840.822185486
1240881.20573598631800.5331132821241038.74476855631674.551449302
#Sta/Elev= 30
 9732.02 184.453 9763.92184.77299767.785184.10169775.517184.6307 9798.71184.6678
9813.163185.28329849.069184.88159861.704183.95289890.811178.44069931.561173.6397
 9948.36173.3566 9972.31171.63289992.257170.850710029.12171.1409 10045.5171.6972
 10049.6171.292210066.24172.897310082.78173.787210095.38176.211710107.99177.4384
10124.02177.663710133.19178.2744 10154.2182.4228   10171188.9735 10179.4191.4873
 10183.6192.139710213.01193.116510234.34193.249810246.62192.429210267.98189.6515
#Mann= 3 , 0 , 0
 9732.02  0.0753       0 9732.02  0.0753       010267.98  0.0753       0
#XS Ineff= 2 , 0
       09935.503                       0
Bank Sta=9732.02,10267.98
Exp/Cntr=0.3,0.1

Type RM Length L Ch R = 1 ,7816.146,188.775700,188.775700,188.775700
XS GIS Cut Line= 4
1240587.33097669632073.9264160541240921.04438317631971.613136694
1241050.10536692631915.1672716591241381.29257825631701.275530994
#Sta/Elev= 30
9609.624176.87679631.947178.25859690.283177.16199755.483169.43129769.209169.8636
9865.293166.95459882.451  167.829913.335167.890110058.18165.492710076.08166.4981
 10101.3166.211710135.43167.471910179.41174.144610195.03175.257110202.84174.4212
10210.65171.702610218.46170.885910323.91173.051110335.63174.761410339.54176.3287
10343.44178.651210355.16188.004810359.06 189.74710362.97190.465710378.59189.5096
10390.31 189.92510429.36198.868310449.89200.144410468.03202.291310493.79201.8278
#Mann= 3 , 0 , 0
9609.624  0.0538       09609.624  0.0538       010493.79  0.0538       0
#XS Ineff= 2 , 0
       0 9945.96        10038.55       0
Bank Sta=9609.624,10493.79
Exp/Cntr=0.3,0.1

Type RM Length L Ch R = 1 , 7627.37,198.616500,198.616500,198.616500
XS GIS Cut Line= 6
1240605.74379274632183.5023851251240901.00513411632133.259750724
1241033.42632559632133.0434377791241069.44166309632129.272474989
 1241140.9610061632111.8124779761241252.83460727632063.009284958
#Sta/Elev= 30
9628.197166.60649661.091164.04439671.067164.19649684.367162.73859691.017162.8674
9707.643161.57299724.268161.92229760.844160.37469774.145 161.065 9784.12160.4786
9800.746160.96229807.396160.51789810.721161.13429833.997161.35899840.647160.4875
9843.972159.12179867.333157.37969900.892157.11919960.307 155.5299973.434153.9481
9989.843152.97879999.693150.794210012.84153.608310039.11154.537410081.88154.1622
10125.13152.565710193.83154.530810254.53158.095510287.49160.588510292.39161.4003
#Mann= 3 , 0 , 0
9628.197   0.085       09628.197   0.085       010292.39   0.085       0
#XS Ineff= 2 , 0
       0                10060.46       0
Bank Sta=9628.197,10292.39
Exp/Cntr=0.3,0.1

Type RM Length L Ch R = 1 ,7428.754,198.616500,198.616500,198.616500
XS GIS Cut Line= 6
1240805.79566476632525.1267650541240983.09259955632379.861412801
1241020.23484012632337.0570822191241054.88049731632277.856301904
1241086.75070643632245.5439881511241288.91562008632115.843269966
#Sta/Elev= 30
9679.755160.77549695.028160.47539708.464159.61389725.066157.82959729.217157.8453
9762.421153.28979770.017152.67899808.077152.36199833.705151.02069883.085149.6653
9908.554148.24769918.119146.67989943.038 145.7299955.536146.29329963.868145.3415
9975.422145.7742  9986.8 145.35110009.56145.533110049.41148.342710122.83150.0865
10164.58150.187210203.26151.502210218.67153.350210230.24155.935110245.66 155.964
10261.07 155.20810280.35155.463210288.06156.834110302.08157.8547 10320.2163.1528
#Mann= 3 , 0 , 0
9679.755  0.0637       09679.755  0.0637       0 10320.2  0.0637       0
#XS Ineff= 2 , 0
       0                10087.38       0
Bank Sta=9679.755,10320.2
Exp/Cntr=0.3,0.1

Type RM Length L Ch R = 1 ,7230.137,198.616500,198.616500,198.616500
XS GIS Cut Line= 6
1240968.66256735632681.8314255251241122.20450128 632526.33426363
1241163.20025763 632471.892915491241203.22738735  632403.5098598
1241257.33078047 632336.334067421241399.63850385 632200.51319449
#Sta/Elev= 30
9675.369145.36779690.164145.56079708.235144.31069721.787145.59679753.411143.1767
9762.446143.48879785.034142.15719808.339142.83479899.077141.12529960.682141.3388
9979.693139.53819991.025136.55079994.803136.240610005.97137.354610017.11139.4398
10028.88139.570810044.74141.194610077.71141.990610099.07144.474410129.17143.2291
10151.48144.787510163.07144.613410183.31146.196510200.33146.398710211.24148.1512
10227.84148.629810245.38152.846510249.76153.495710297.99159.617810324.68162.2428
#Mann= 3 , 0 , 0
9675.369  0.0732       09675.369  0.0732       010324.68  0.0732       0
#XS Ineff= 2 , 0
       09937.676                       0
Bank Sta=9675.369,10324.68
Exp/Cntr=0.3,0.1

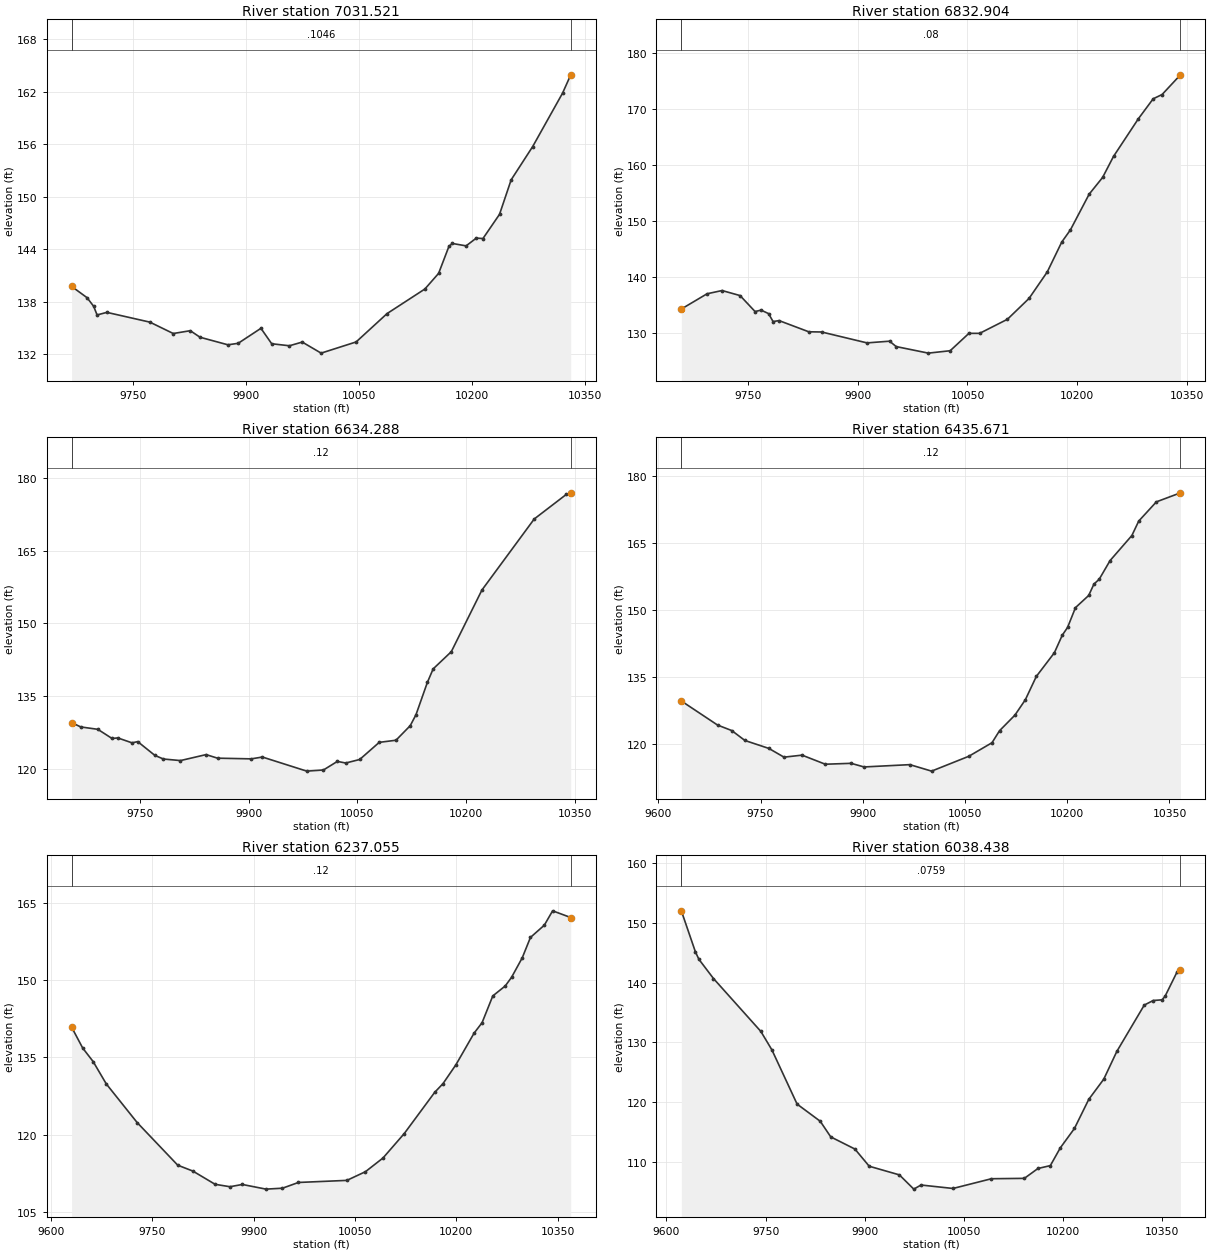
Type RM Length L Ch R = 1 ,7031.521,198.616500,198.616500,198.616500
XS GIS Cut Line= 6
1241088.77627199632780.9810165971241182.64611236632697.632509308
1241304.09998049632581.8356042041241366.05800423632532.941911662
1241481.60753359632421.3590482751241578.08067689632335.139303015
#Sta/Elev= 30
9668.849 139.7729689.313138.48389698.088137.50129702.628136.51459715.638136.8074
9772.676135.69339803.687134.39519826.352134.71529839.223133.96869876.215133.1063
9889.814133.27479920.049134.98829934.313133.2264 9957.81132.99569974.872 133.418
9999.926132.155110046.36133.432110087.41136.668910137.58139.474410155.82141.2602
 10169.5144.341110174.06144.674210192.31144.399610205.84145.286510214.64145.2359
10236.64148.000810252.08151.938810280.64 155.73710320.24161.828810331.14163.9248
#Mann= 3 , 0 , 0
9668.849  0.1046       09668.849  0.1046       010331.14  0.1046       0
#XS Ineff= 2 , 0
       09951.377                       0
Bank Sta=9668.849,10331.14
Exp/Cntr=0.3,0.1

Type RM Length L Ch R = 1 ,6832.904,198.616500,198.616500,198.616500
XS GIS Cut Line= 6
1241164.53076685632902.3639777011241354.76442008632762.591635306
1241450.93737155632704.8029653771241507.41682955632676.722800269
1241557.11249295632647.2995657781241731.29570876632524.014865883
#Sta/Elev= 30
9658.703134.32539693.885137.04429714.401137.62099739.021136.72359759.537133.8767
9767.743 134.1329777.977133.51019784.156132.09239792.363132.26389832.971130.2685
9850.501130.23479912.645  128.29  9943.5128.59569952.511127.63319996.467126.4662
10026.36 126.893   10052129.990510066.66129.991610104.65132.498410134.25136.2195
10159.16140.942410178.94146.2571 10190.8148.430210216.42154.793810234.84157.7801
10249.74 161.52510283.64168.218410303.97171.791910316.17172.555510341.29176.0646
#Mann= 3 , 0 , 0
9658.703    0.08       09658.703    0.08       010341.29    0.08       0
#XS Ineff= 2 , 0
       0 9929.58                       0
Bank Sta=9658.703,10341.29
Exp/Cntr=0.3,0.1

Type RM Length L Ch R = 1 ,6634.288,198.616500,198.616500,198.616500
XS GIS Cut Line= 6
1241270.77462837633055.0360660241241461.27584672632928.632432989
1241559.95156927632869.2372552171241651.05740058632812.927402621
1241750.36400766632745.7846890011241847.38692682632677.193833468
#Sta/Elev= 30
9655.204129.54689667.768128.64979691.393128.15659711.079126.26599718.954126.3837
9738.641125.37129746.516125.61999770.134122.79049781.952122.03449805.576121.7117
9841.013122.94319856.762122.20739903.457122.06499918.774 122.4429980.043119.5355
10003.08119.767610022.36121.539810033.93121.209510053.21121.9343 10080.2125.4684
10103.33125.905710123.06128.912810130.98131.169610146.82137.877210154.74140.6243
10179.75144.159210222.07156.875710294.33 171.52910338.53176.5834 10344.8176.9261
#Mann= 3 , 0 , 0
9655.204    0.12       09655.204    0.12       0 10344.8    0.12       0
#XS Ineff= 2 , 0
       09864.789                       0
Bank Sta=9655.204,10344.8
Exp/Cntr=0.3,0.1

Type RM Length L Ch R = 1 ,6435.671,198.616500,198.616500,198.616500
XS GIS Cut Line= 6
1241352.73558679633209.6419220421241598.82175998633063.537916313
1241708.53400456633011.6584890371241783.65515078632969.807971894
1241885.38570968632906.1294950531241982.83643778632838.451445304
#Sta/Elev= 30
9633.825129.67599686.988 124.2969707.822 123.0679727.083120.85319762.212 119.079
9784.451117.12499810.965117.57549845.054115.54659882.931115.74789901.869114.9369
9969.113115.4526   10001114.004210055.62117.321610089.66120.352710100.68123.0309
10123.22126.508110138.57129.953710154.63135.154810181.14140.449410192.76144.3817
 10200.5 146.10410212.11150.531510231.46153.2446 10239.2155.791110246.94156.8783
 10262.9161.050310294.86166.643910304.91169.869610330.81174.165110366.14176.1812
#Mann= 3 , 0 , 0
9633.825    0.12       09633.825    0.12       010366.14    0.12       0
#XS Ineff= 2 , 0
       0                               0
Bank Sta=9633.825,10366.14
Exp/Cntr=0.3,0.1

Type RM Length L Ch R = 1 ,6237.055,198.616500,198.616500,198.616500
XS GIS Cut Line= 6
1241437.97883862633386.0420413621241546.15063751633320.777057481
1241717.40134226633231.8961643641241796.14236945633170.300403027
1241947.29050271633079.640020451 1242063.8741043632996.802301118
#Sta/Elev= 30
9630.642140.87149647.028 136.8119662.533134.17259681.915129.84569727.588122.3341
9787.711114.04089810.033112.90319843.016110.3268 9864.99109.85689883.302110.2963
9918.287109.39039942.676109.56979966.273110.6849   10038111.089910065.56 112.783
10091.49115.443210122.94 120.19110168.03128.207410180.33129.903510199.46133.5772
10226.28139.706210238.12 141.73910253.97146.939910272.34148.870510281.69150.5413
10297.54154.341210309.72158.309410330.21 160.68510342.51163.477410369.34162.1768
#Mann= 3 , 0 , 0
9630.642    0.12       09630.642    0.12       010369.34    0.12       0
#XS Ineff= 2 , 0
       0                               0
Bank Sta=9630.642,10369.34
Exp/Cntr=0.3,0.1

Type RM Length L Ch R = 1 ,6038.438,198.616500,198.616500,198.616500
XS GIS Cut Line= 6
1241502.52895841633595.3629200341241699.60883912633445.115354442
1241858.27181863633361.5986169691241914.38470623633325.807156745
1241999.83101232633257.9727092841242111.86026459633155.686363852
#Sta/Elev= 30
9622.581152.01039643.832145.15349649.067143.90859671.221140.67649742.801131.8286
9759.553128.73319797.651119.65769832.626116.7907 9848.55114.16959885.062112.1371
9906.704109.25939952.347107.81199974.133105.42729985.026106.1155 10033.4105.5383
10091.55107.167510141.33  107.23 10161.9108.881910180.63109.363910195.72112.3392
10217.05115.576910238.74120.4509 10261.4123.828810281.18128.4764 10322.7136.2363
10336.19136.998710349.67137.112710354.16 137.71610372.14141.752410377.41142.1422
#Mann= 3 , 0 , 0
9622.581  0.0759       09622.581  0.0759       010377.41  0.0759       0
#XS Ineff= 2 , 0
       0                               0
Bank Sta=9622.581,10377.41
Exp/Cntr=0.3,0.1

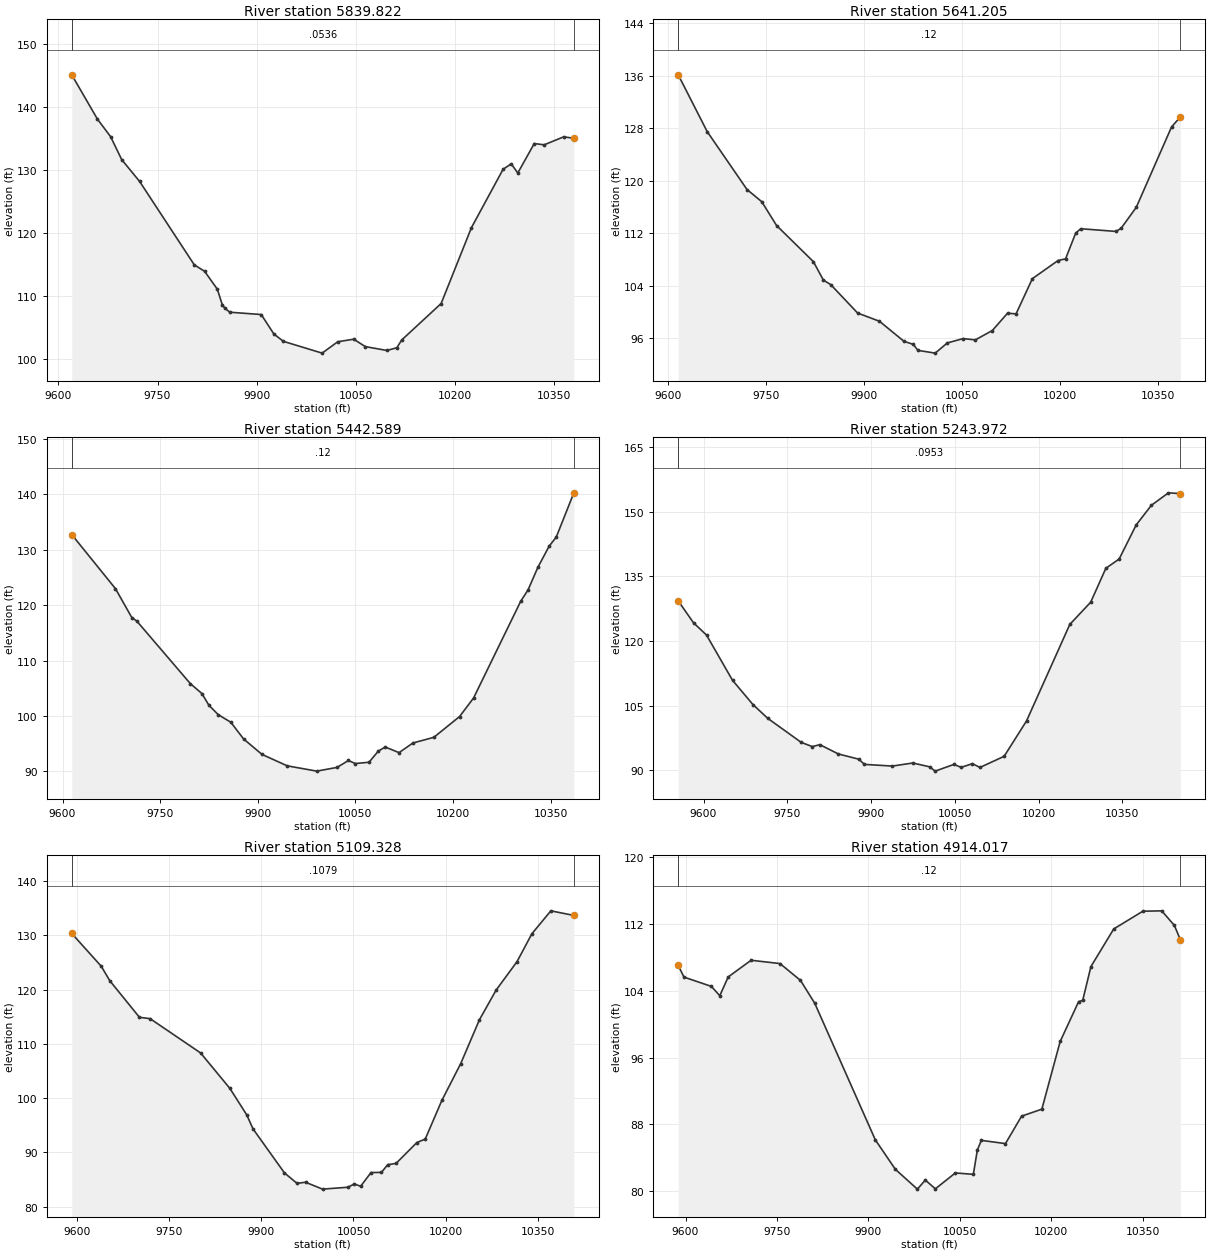
Type RM Length L Ch R = 1 ,5839.822,198.616500,198.616500,198.616500
XS GIS Cut Line= 6
1241782.91590384633814.0785064791241932.89353269 633582.46609852
1241959.44249838633522.330445997 1241986.8130471633428.169160536
1242017.69356802633367.8442826291242176.99142526633173.476963614
#Sta/Elev= 30
 9620.28 145.1249659.065138.08459679.007135.29369695.807 131.6439722.879 128.174
9805.677114.89389821.146113.8871 9840.47111.03479847.992108.55369851.754108.0257
9859.276107.37279906.843107.00619925.987103.91429940.335102.7422    9999100.8684
10022.58102.678510046.78103.081910064.29101.905510096.82 101.29310111.94101.7194
 10119.5102.976310178.98108.757810224.82120.822710272.73130.111210284.99130.9654
10294.95129.513910319.85134.198710334.79133.993210364.32135.260710379.72135.0375
#Mann= 3 , 0 , 0
 9620.28  0.0536       0 9620.28  0.0536       010379.72  0.0536       0
#XS Ineff= 2 , 0
       0                               0
Bank Sta=9620.28,10379.72
Exp/Cntr=0.3,0.1

Type RM Length L Ch R = 1 ,5641.205,198.616500,198.616500,198.616500
XS GIS Cut Line= 6
1241942.50998588633922.0132321181241997.68605085633828.146093609
1242072.72843031633694.9072215511242129.60830264633585.828925071
1242150.69066642633546.5604287681242328.88663033633259.046436533
#Sta/Elev= 30
9616.181136.12669660.415127.48199721.305118.65349743.938116.7909 9766.53113.1663
9822.859107.65589838.073104.85179849.369104.15949890.42899.832039923.87498.57522
9961.34695.51753 9975.5395.057059982.62294.1423910009.02 93.720910027.6495.27498
10051.7595.9334210070.4395.7404510096.4697.1674110119.6299.7987610132.7199.70613
10157.62105.067510196.82107.8277 10208.4108.088710223.84112.003410231.56112.6762
 10285.6112.266110293.32112.745310316.47115.932610370.51128.198710383.83129.7023
#Mann= 3 , 0 , 0
9616.181    0.12       09616.181    0.12       010383.83    0.12       0
#XS Ineff= 2 , 0
       0                10160.22       0
Bank Sta=9616.181,10383.83
Exp/Cntr=0.3,0.1

Type RM Length L Ch R = 1 ,5442.589,198.616500,198.616500,198.616500
XS GIS Cut Line= 6
1242155.91947641634030.0998393461242256.71025322633804.459795191
1242291.21885728633717.9148281381242324.60612416633623.182113659
1242362.75955775633530.7966439031242460.29528242633321.489281582
#Sta/Elev= 30
9614.163132.74759681.322122.9899 9706.64117.73399713.874117.17199796.284105.8635
9814.142104.06639824.858101.95859839.145100.26089858.63698.877179878.24495.86437
  9906.593.077989945.35291.00944 9990.6790.0574610021.9890.7294910039.3991.98227
10049.8491.4278410071.0491.6597710085.2493.6616110095.8994.4109610117.19 93.3957
10138.49  95.13410170.6396.1562410210.1799.9047710231.74103.260610304.07120.6931
10315.42122.757510330.44126.810710347.84130.654310358.78132.292810385.83140.2865
#Mann= 3 , 0 , 0
9614.163    0.12       09614.163    0.12       010385.83    0.12       0
#XS Ineff= 2 , 0
       0                10099.16       0
Bank Sta=9614.163,10385.83
Exp/Cntr=0.3,0.1

Type RM Length L Ch R = 1 ,5243.972,134.644300,134.644300,134.644300
XS GIS Cut Line= 4
1242420.85243601634166.7803264561242485.24994934633782.695157766
1242535.84799552633518.2053709331242597.94559762633285.914340764
#Sta/Elev= 30
9554.685129.31119582.058124.22899605.344121.37479651.917110.8665 9688.51105.2289
9715.123102.02099775.00296.441489794.96295.463779808.26995.918119841.53593.75407
9878.12892.542529888.10891.337579938.00790.943779974.72691.6560610004.79 90.7728
10014.8189.7697510048.2191.3223310061.5790.6461510081.6291.5113610094.9890.61878
 10138.493.2169810178.49 101.43810256.01 123.85910293.37129.013710320.54  136.89
10344.31139.035710374.87146.965610402.04151.521210432.61154.418710453.87154.2396
#Mann= 3 , 0 , 0
9554.685  0.0953       09554.685  0.0953       010453.87  0.0953       0
#XS Ineff= 2 , 0
       0                10080.91       0
Bank Sta=9554.685,10453.87
Exp/Cntr=0.3,0.1

Type RM Length L Ch R = 1 ,5109.328,195.311100,195.311100,195.311100
XS GIS Cut Line= 6
1242495.98054046634161.9629003581242543.08549496634025.244305847
1242606.11552956633811.259013826 1242635.1027832633724.438531533
1242700.17687269633483.0310428821242733.10138339 633378.98919302
#Sta/Elev= 30
9590.799130.34879638.847124.31159652.768 121.6459701.159114.89859718.442114.6597
9800.705108.34629848.588101.79589875.94996.93906 9886.2194.349919937.51386.22936
9958.03484.310269971.862 84.51649999.535 83.248110041.0583.5950710051.3984.21141
10061.5983.7666310078.5886.3063810095.5786.3281510105.7687.7546110119.3587.98474
10153.3391.8354510166.9292.4672710194.11  99.60910224.69106.353410255.27114.4465
10282.45119.910510316.64125.174710340.73130.2873 10371.7 134.52110409.18133.6722
#Mann= 3 , 0 , 0
9590.799  0.1079       09590.799  0.1079       010409.18  0.1079       0
#XS Ineff= 2 , 0
       0                               0
Bank Sta=9590.799,10409.18
Exp/Cntr=0.3,0.1

Type RM Length L Ch R = 1 ,4914.017,195.311100,195.311100,195.311100
XS GIS Cut Line= 6
1242737.27493129634204.5033329761242800.64611963633971.561469237
1242811.12704428 633881.905541751242817.51658531633648.300626349
1242840.29557754633535.4835404091242881.52042538633398.904273886
#Sta/Elev= 30
9588.049107.01679597.474105.62499642.413104.51149656.241103.39559670.056105.6434
9707.576107.63969755.045107.24439788.675105.2308 9812.09102.49179911.46686.14307
9944.31482.62096 9980.4280.246329993.55381.3279510009.9780.28298 10042.882.18338
10072.3482.0159710078.91 84.939210085.4986.0820310125.0385.6964910151.4688.97797
10184.7489.8195710214.8197.9186910245.07102.686810251.79102.838110265.24 106.881
10302.69111.387610350.41113.508110381.46113.5566 10402.2111.811910411.95 110.111
#Mann= 3 , 0 , 0
9588.049    0.12       09588.049    0.12       010411.95    0.12       0
#XS Ineff= 2 , 0
       09907.943                       0
Bank Sta=9588.049,10411.95
Exp/Cntr=0.3,0.1

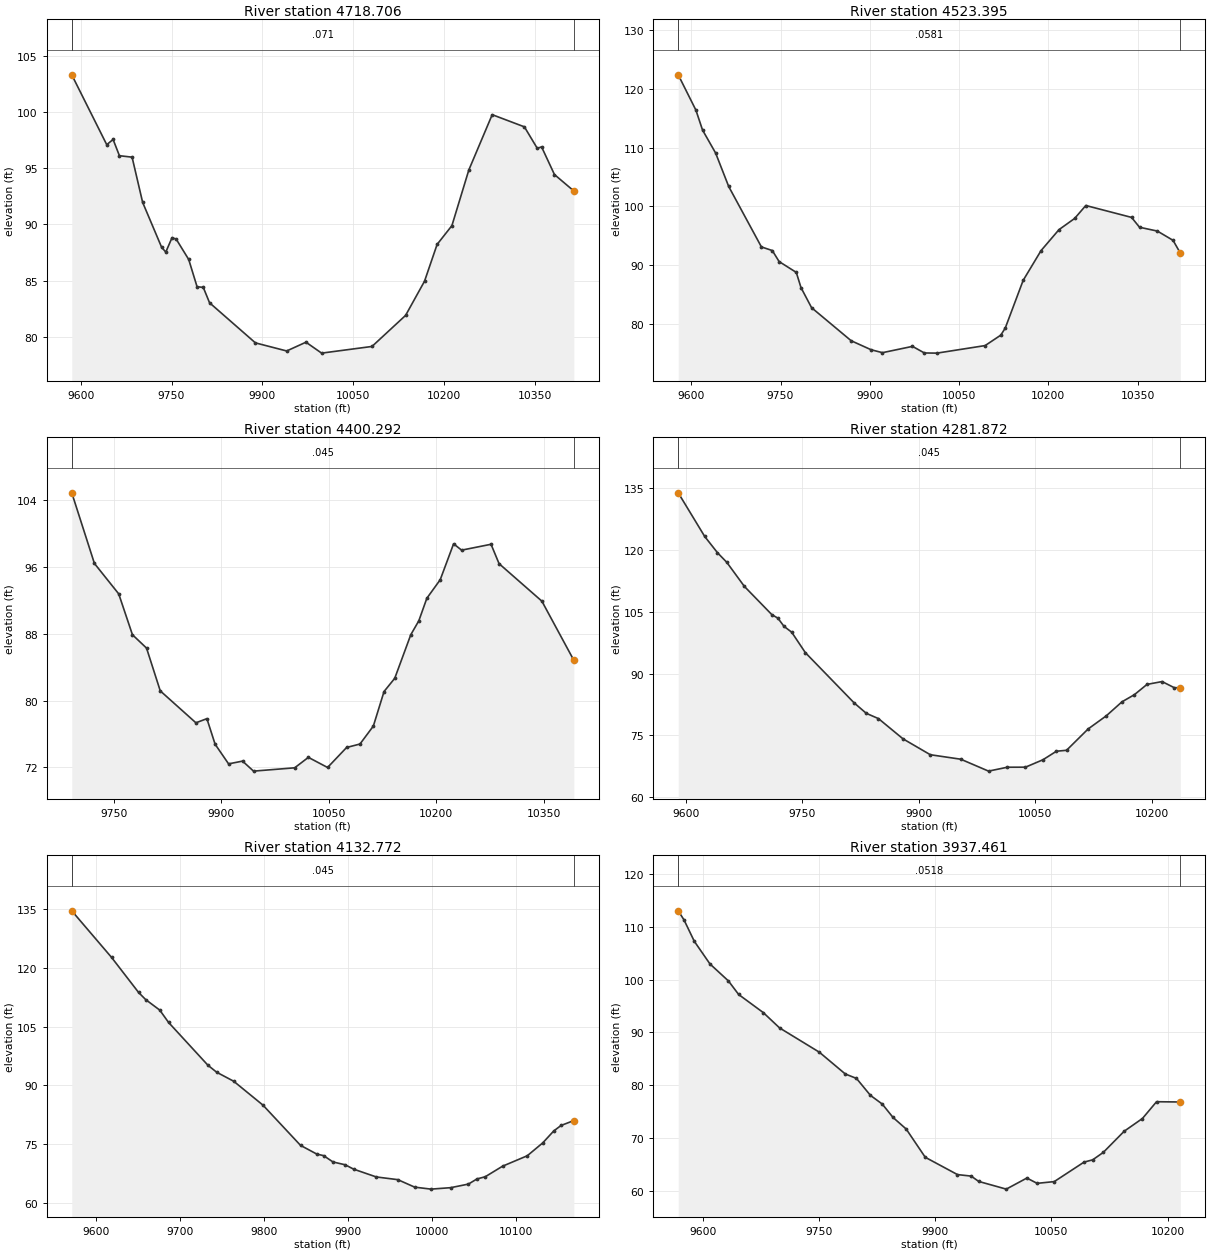
Type RM Length L Ch R = 1 ,4718.706,195.311200,195.311200,195.311200
XS GIS Cut Line= 6
1242861.50426514634219.8229126951242912.93144979634082.396966366
1242982.38611011633865.780492622 1243018.3376718633780.183264382
1243091.44669588633574.1058684841243146.33923578 633440.86417145
#Sta/Elev= 30
9585.064103.30039642.88497.086379653.35497.552999663.81996.107129684.74895.97681
 9702.1991.956569733.56387.963559740.45387.532559750.78988.81682 9757.6888.68665
9778.352 86.87629792.13484.45724 9802.47 84.38899812.80683.024929888.60479.45823
9940.28478.738299972.15179.518969998.03178.5467110081.2979.1401410136.8481.90428
10168.0984.9402810188.9288.21683 10213.489.8891710241.3794.8407510279.9799.75659
 10333.298.6728410354.4996.7609210361.5896.8929710382.8794.4291810414.9292.96976
#Mann= 3 , 0 , 0
9585.064   0.071       09585.064   0.071       010414.92   0.071       0
#XS Ineff= 2 , 0
       0 9927.55                       0
Bank Sta=9585.064,10414.92
Exp/Cntr=0.3,0.1

Type RM Length L Ch R = 1 ,4523.395,123.102300,123.102300,123.102300
XS GIS Cut Line= 6
1242970.74279704634281.3147269851243113.03311212633999.354213405
 1243143.9384152633947.3146834271243190.11035469633881.913350816
1243218.02287512633837.3634886151243381.63137095633545.165578774
#Sta/Elev= 30
9578.064122.41639607.789116.4007 9618.89113.02179640.882109.10289662.874 103.404
9717.85493.11642 9736.1892.497149747.59990.622349776.49988.776279784.39186.18732
9802.156 82.77169868.70977.140629902.28875.604319921.36775.108919971.78176.18142
9991.79375.05845 10012.975.0309510093.9176.3170710120.2378.0951110127.7579.30766
10157.83 87.423710187.9192.49021   1021896.0541110244.3297.9623810263.12100.1661
10340.0298.1405310353.3696.4648310383.4495.8105710409.7694.2349410421.9592.06575
#Mann= 3 , 0 , 0
9578.064  0.0581       09578.064  0.0581       010421.95  0.0581       0
#XS Ineff= 2 , 0
       09939.847                       0
Bank Sta=9578.064,10421.95
Exp/Cntr=0.3,0.1

Type RM Length L Ch R = 1 ,4400.292,118.420700,118.420700,118.420700
XS GIS Cut Line= 3
1243120.95684972634229.2109473941243312.71324605633909.185069799
1243468.19140521633621.550475329
#Sta/Elev= 30
9691.724 104.8199723.30696.379589757.17992.744349776.32887.860039795.97586.26568
9815.09981.15392 9864.8277.337029880.11977.832299891.59374.776969910.37472.42932
 9929.8472.760859945.13971.5626210002.5171.9581510021.6373.2073710048.4171.99732
10074.9274.3881410093.5774.8014910112.22 76.948210127.1381.0767510142.0582.65434
10164.4387.8634610175.6289.52603 10186.8 92.220410205.4594.43303 10224.198.72571
10235.2997.9675610276.3198.67111 10287.596.3552310347.1791.8757910391.7784.80491
#Mann= 3 , 0 , 0
9691.724   0.045       09691.724   0.045       010391.77   0.045       0
#XS Ineff= 2 , 0
       09925.579                       0
Bank Sta=9691.724,10391.77
Exp/Cntr=0.3,0.1

Type RM Length L Ch R = 1 ,4281.872,149.099200,149.099200,149.099200
XS GIS Cut Line= 6
1243153.10711896634368.4023152941243362.94912528634049.033850591
1243388.71183166634012.6661624711243389.95631986634011.100515925
1243415.88808031633974.9286615251243513.37670026633831.670402607
#Sta/Elev= 30
9590.037133.80479624.123123.22719640.552119.29099652.501116.97329675.157 111.136
9710.488104.29399718.339103.42759726.191101.45069736.147 100.021 9753.6795.07975
9816.48182.900899832.183 80.36169847.88679.079149879.53874.167859914.62270.32598
9953.87969.235949989.62266.3510110013.7567.2965110037.1267.3077410059.6469.10451
10077.0171.1731410090.0571.4009410117.8276.5713410141.1679.7457710161.4883.15782
10177.35 84.873110193.6487.3729410213.07 88.058310228.9486.5550610236.53 86.5932
#Mann= 3 , 0 , 0
9590.037   0.045       09590.037   0.045       010236.53   0.045       0
#XS Ineff= 2 , 0
       0                               0
Bank Sta=9590.037,10236.53
Exp/Cntr=0.3,0.1

Type RM Length L Ch R = 1 ,4132.772,195.311100,195.311100,195.311100
XS GIS Cut Line= 6
1243216.61589674634444.2667882581243329.98203145634304.523637622
1243392.05387463634233.9955416791243477.93625458634141.508313893
1243518.63046902634089.0082927531243604.33408788633990.508786341
#Sta/Elev= 30
9571.223134.57239618.598122.67169650.674113.74789659.123111.92059675.882109.2375
9686.298106.10469733.16695.166819743.58193.382189763.79791.085989798.55984.99889
9843.252 74.72939862.59272.50339 9870.7172.100179881.87870.491819896.34369.76651
9906.52868.646279933.39166.663119959.02265.97093 9979.0564.060639998.48663.55559
10021.93 63.928210042.9764.8443610053.0866.1501310062.9766.7150310083.53 69.4043
10112.9572.0705510131.3675.3597410144.41 78.396910153.1179.8013610168.3381.05038
#Mann= 3 , 0 , 0
9571.223   0.045       09571.223   0.045       010168.33   0.045       0
#XS Ineff= 2 , 0
       0                               0
Bank Sta=9571.223,10168.33
Exp/Cntr=0.3,0.1

Type RM Length L Ch R = 1 ,3937.461,195.311100,195.311100,195.311100
XS GIS Cut Line= 6
1243320.84996979634571.905909926  1243408.049494634474.497446551
1243497.67485539634379.4884579431243579.51733381634298.212747611
1243673.93180505634212.3889346461243775.94221419 634111.15449938
#Sta/Elev= 30
 9568.37112.99969575.904111.25949589.114107.22999609.329102.94299633.14899.72896
9646.35897.162459678.193 93.72939699.20190.832579750.49786.239969783.965 82.1183
9798.42681.277029816.46778.064759831.70976.42131 9845.5873.890639862.59971.69418
9887.19466.349239928.808 63.07049946.46362.787399956.16461.778589991.76560.32092
10018.3462.4189810031.5961.4164710053.6961.7446510092.12 65.4341 10103.365.86579
10117.01 67.278710143.9871.2839410167.4873.6883210185.7276.8673410216.39  76.814
#Mann= 3 , 0 , 0
 9568.37  0.0518       0 9568.37  0.0518       010216.39  0.0518       0
#XS Ineff= 2 , 0
       0                               0
Bank Sta=9568.37,10216.39
Exp/Cntr=0.3,0.1

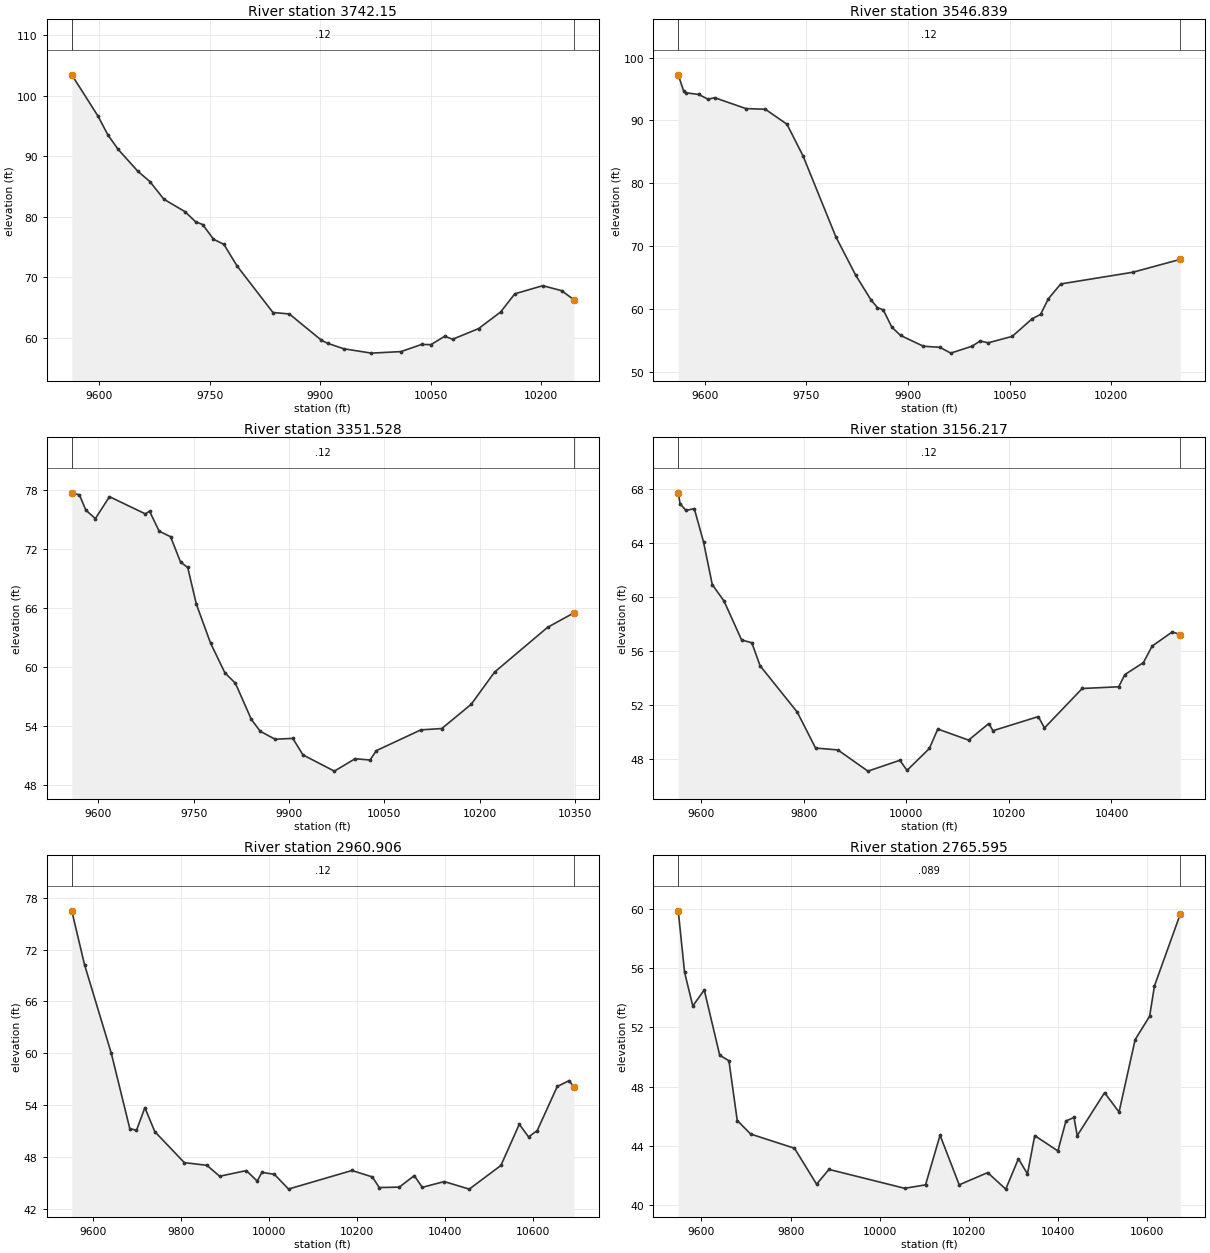
Type RM Length L Ch R = 1 , 3742.15,195.311200,195.311200,195.311200
XS GIS Cut Line= 6
1243468.82449678634723.4240731331243687.67121553634488.236586097
1243733.27039532634434.1279462091243777.11743297634371.095862734
1243822.52592443634315.329382235 1243917.1188008634210.405917848
#Sta/Elev= 30
9562.601103.45079598.25996.629029611.81193.497219625.71891.131479652.46787.51711
9668.67385.837489687.76582.911839716.40280.864099730.782  79.1939740.50878.72851
9755.097 76.31479769.23475.463989787.01471.916059835.90664.21318 9858.1363.97583
 9901.7959.631299910.50959.112049931.96258.23121 9969.5657.50622 10009.857.75924
10037.7958.9379310050.4858.9105410069.1360.28442 10080.159.8019110115.2361.55978
 10145.2 64.306510164.4267.3004810202.4368.64238 10228.167.8129310244.6166.32498
#Mann= 3 , 0 , 0
9562.601    0.12       09562.601    0.12       010244.61    0.12       0
#XS Ineff= 2 , 0
       0                               0
Bank Sta=9562.601,10244.61
Exp/Cntr=0.3,0.1

Type RM Length L Ch R = 1 ,3546.839,195.311100,195.311100,195.311100
XS GIS Cut Line= 6
 1243611.5956848634853.1910523431243809.66657144634648.966812968
1243865.48294655634580.5615976941243927.12502249634487.561881771
1243968.90833587634434.1616001771244093.94815299634293.401289739
#Sta/Elev= 30
9561.115 97.26479568.971 94.72939572.564  94.4029591.28194.139989605.31993.36935
9614.67793.625239660.99991.887519689.54491.785859721.50689.394479745.28384.32727
9793.61271.46342 9822.8365.366479845.70561.365649855.01760.184259863.48659.83082
9876.189 57.0817 9888.9655.766419922.76854.038119947.22653.86956 9963.0352.94261
9994.63954.0489310006.4554.8843310018.1954.5806510053.7455.6115110083.0758.40758
10095.5759.1181910106.9861.5879910125.28 63.958810231.6565.8246610301.6767.87788
#Mann= 3 , 0 , 0
9561.115    0.12       09561.115    0.12       010301.67    0.12       0
#XS Ineff= 2 , 0
       0                               0
Bank Sta=9561.115,10301.67
Exp/Cntr=0.3,0.1

Type RM Length L Ch R = 1 ,3351.528,195.311100,195.311100,195.311100
XS GIS Cut Line= 6
1243733.18735892634948.1948606821243839.38594592634856.105772465
1243922.32022056634778.3543499261244053.39142087634646.081130549
1244172.18344685634524.3384357391244203.28360814634348.473310471
#Sta/Elev= 30
9558.53977.753599570.57877.544459580.594  76.0039595.61875.129079617.79877.36287
9674.25175.609059680.75175.883069695.963 73.8514 9713.8473.291349729.49470.71162
9740.82370.159419754.31466.43678  9776.862.452199799.28659.439629815.72558.39357
9840.74454.717769854.72753.507389878.03352.69672    990652.779589921.95751.09888
9971.25549.4503810003.9150.71009 10027.4 50.581510037.1451.5312410107.2753.64623
10140.1653.7837210186.4656.2554210223.1159.5233210306.4164.0766410347.69 65.5409
#Mann= 3 , 0 , 0
9558.539    0.12       09558.539    0.12       010347.69    0.12       0
#XS Ineff= 2 , 0
       0                10136.12       0
Bank Sta=9558.539,10347.69
Exp/Cntr=0.3,0.1

Type RM Length L Ch R = 1 ,3156.217,195.311100,195.311100,195.311100
XS GIS Cut Line= 6
1243837.65357858635047.3322788031244134.94402725634836.229805425
1244166.84387577634808.7228185091244228.46778426634746.861878619
1244273.80944771634705.5829638091244518.37144113634359.972866431
#Sta/Elev= 30
9555.39967.683579558.94866.886139570.37566.377259586.67666.519289604.65564.05891
9621.79660.895339644.64959.68254 9678.9356.805969698.88356.595019714.91254.90136
9787.48551.468569823.11248.813049866.61748.672999925.19747.106059987.47447.90915
10001.4147.1612110045.0348.7826110061.3950.2197810121.3849.3998210160.8650.62441
 10168.950.0937510257.32 51.138610269.3850.29816 10342.953.2160910414.0753.34226
10426.1254.2467610462.1755.1269910479.2156.3498610518.56 57.401310534.1857.19895
#Mann= 3 , 0 , 0
9555.399    0.12       09555.399    0.12       010534.18    0.12       0
#XS Ineff= 2 , 0
       0                10135.75       0
Bank Sta=9555.399,10534.18
Exp/Cntr=0.3,0.1

Type RM Length L Ch R = 1 ,2960.906,195.311100,195.311100,195.311100
XS GIS Cut Line= 6
1243877.71623054635159.447156966 1244028.6386956 635069.79218246
1244119.46847874635020.5017038881244336.34649745634926.204145759
1244400.28334936634894.2962964031244879.45749792634612.963097274
#Sta/Elev= 30
9550.839 76.49229579.81770.274019640.87459.99142 9682.85 51.29689698.115  51.092
9717.19553.715769739.792   50.949806.98247.354369858.393  47.0439887.39745.77827
9948.05446.434249972.888 45.21519983.53246.22893   1001245.9980710044.1444.29575
10188.36  46.44310234.9645.6966510250.5544.4708310296.2644.5178310330.2545.85143
10348.5444.4947210398.5345.1621410455.4344.2869110527.5147.0293910569.2451.79637
10590.3450.3361810609.9551.0505810655.6956.1664810683.0556.8512410693.4356.06027
#Mann= 3 , 0 , 0
9550.839    0.12       09550.839    0.12       010693.43    0.12       0
#XS Ineff= 2 , 0
       09918.338         10149.3       0
Bank Sta=9550.839,10693.43
Exp/Cntr=0.3,0.1

Type RM Length L Ch R = 1 ,2765.595,195.311200,195.311200,195.311200
XS GIS Cut Line= 6
 1243971.9564608635330.0893113761244138.84802142 635243.04380016
 1244322.8438631635133.9955631491244420.21885124635096.886808544
1244661.11999041634909.1753182261244946.15492243634778.556702957
#Sta/Elev= 30
9548.01359.84545 9562.2455.700859580.62653.433679606.36654.509919641.04750.11045
9661.69349.740839680.33545.711559710.52244.79725 9808.7243.840879858.29941.41751
9886.02442.4161310055.8341.14086 10102.641.3743410135.18 44.717710178.0741.37619
10241.9642.1993210282.4541.0857710310.89 43.133510331.1942.1136310347.4444.69299
10399.4143.6598410417.4545.67855 10435.545.9186510442.7244.6907810504.0747.58563
10536.5546.2833710572.64 51.163610605.1252.7395810615.9454.7846110673.9359.63235
#Mann= 3 , 0 , 0
9548.013   0.089       09548.013   0.089       010673.93   0.089       0
#XS Ineff= 2 , 0
       09917.316        10143.39       0
Bank Sta=9548.013,10673.93
Exp/Cntr=0.3,0.1