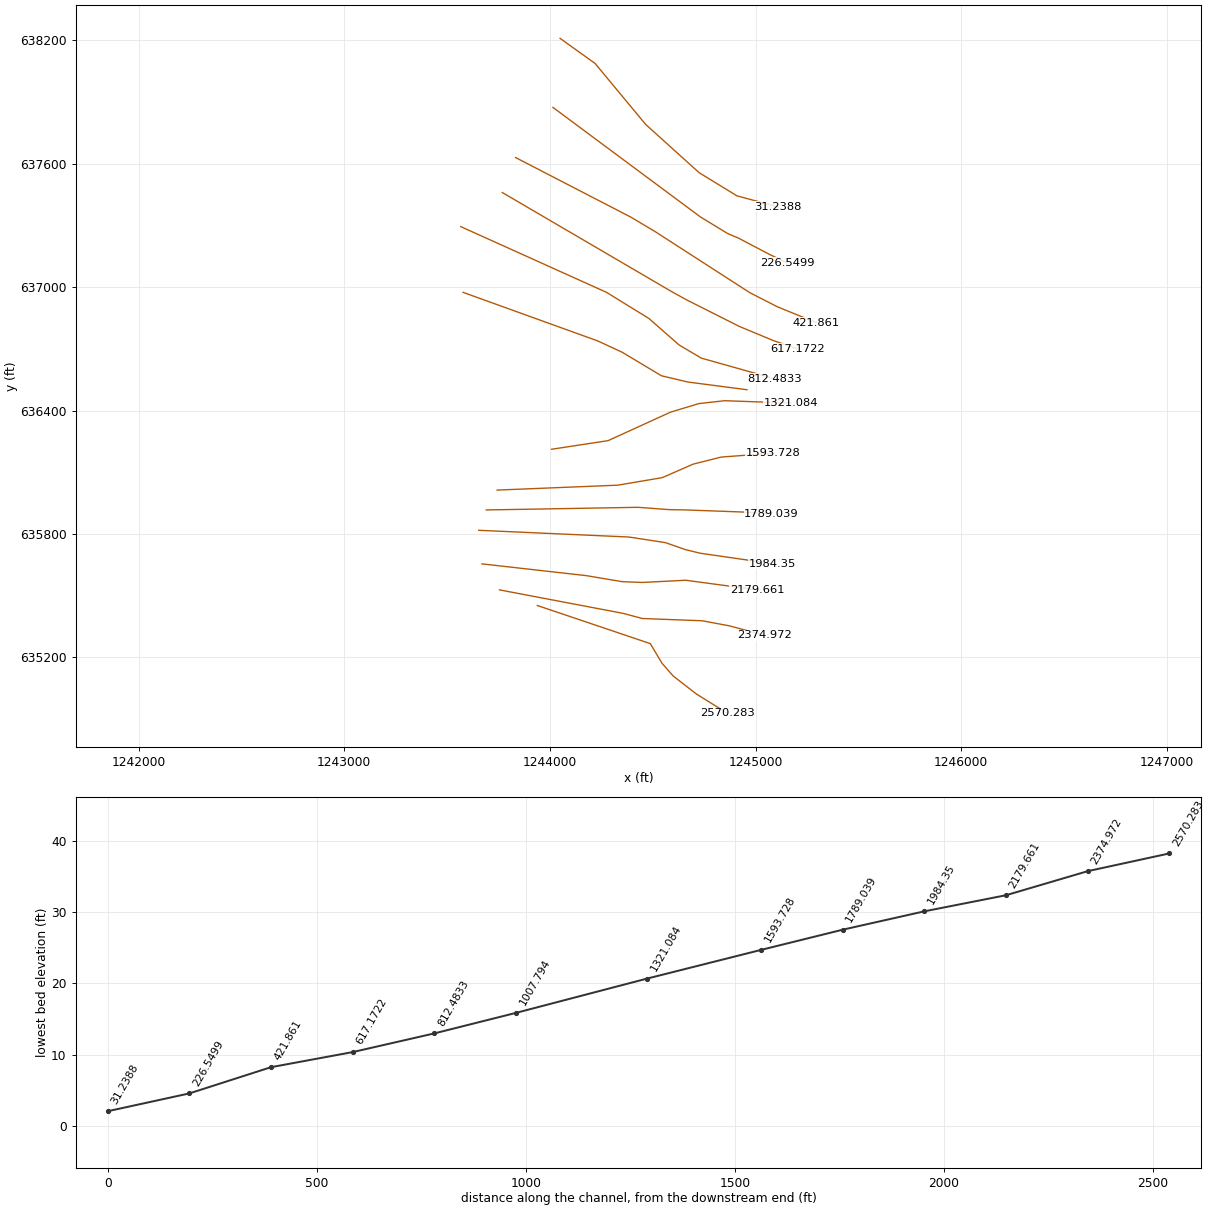
HEC-RAS study 712_ras.prj: 712

--- 712_ras.g01 (geometry) --- (continued)

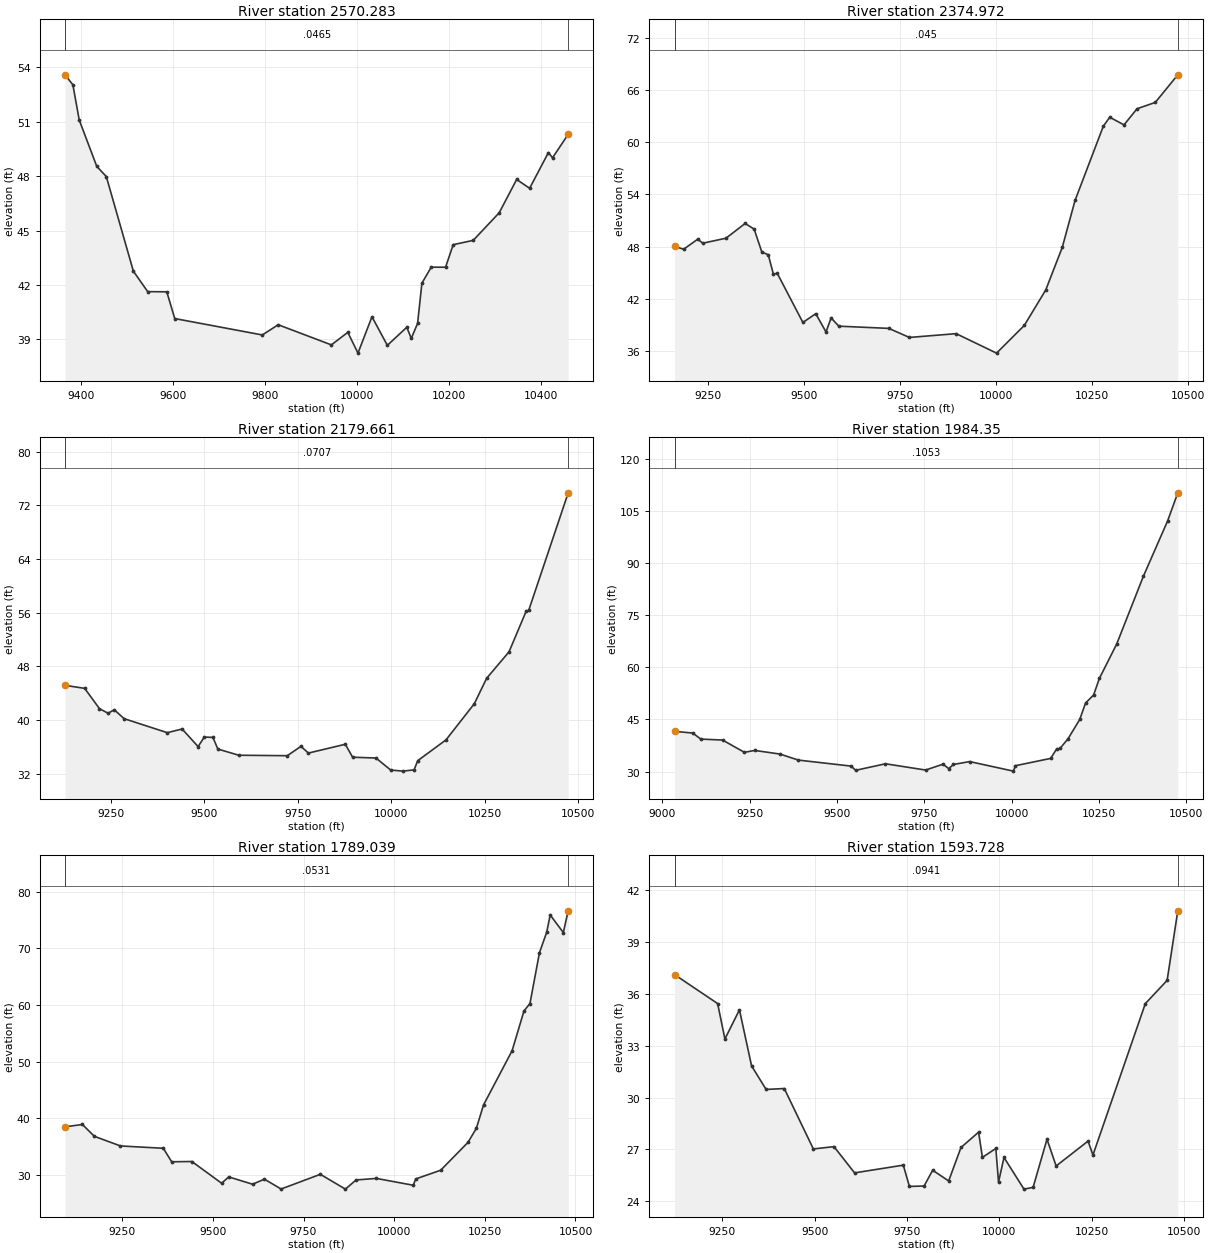
Type RM Length L Ch R = 1 ,2570.283,195.311100,195.311100,195.311100
XS GIS Cut Line= 6
1243938.79382128635452.430681571 1244487.8968792635267.132233486
1244545.35632572635170.9749695061244599.73744324635109.224482968
1244712.25013775635022.1071345211244863.62646556634927.962532297
#Sta/Elev= 30
9365.547 53.5948 9382.7853.046159396.63151.099849434.71948.546659455.49547.98167
9514.35942.762489545.52341.632559587.07441.622239604.38740.14723 9794.8339.24198
9829.45639.805469945.07238.69441 9980.8439.3860910002.95 38.2395 10033.440.24696
10066.8238.6692510109.17 39.667710118.86 39.050810132.6339.8788410142.0342.09941
10162.2842.9819810193.5242.9798610210.0344.22299 10253.6 44.4606 10310.245.98428
10348.1347.8211110376.3647.3346710417.2349.3077310426.1449.0162110460.2650.31245
#Mann= 3 , 0 , 0
9365.547  0.0465       09365.547  0.0465       010460.26  0.0465       0
#XS Ineff= 2 , 0
       09799.708                       0
Bank Sta=9365.547,10460.26
Exp/Cntr=0.3,0.1

Type RM Length L Ch R = 1 ,2374.972,195.311100,195.311100,195.311100
XS GIS Cut Line= 6
1243754.80092612635528.3277508321244354.71026945635414.484261647
1244449.48106155635389.1987137651244739.78386104635378.272526368
1244871.11155057635353.8527433281245041.61927241635308.372268543
#Sta/Elev= 30
9163.11248.032379186.68247.686569223.41548.841849236.77348.386129296.88248.95571
9346.97250.654129370.34850.000629390.38447.363899407.08147.058429420.43944.83298
9430.457 44.92449497.24539.274559530.63840.283459557.35438.188389570.71139.79396
9590.74738.849459720.983 38.5954 9774.4337.553759896.14837.9898110001.32 35.7519
10073.5338.9346410129.4343.0150310172.3847.9055110205.61 53.296410279.1661.82146
10295.9262.8597910333.1361.9835810366.9563.8332210414.5464.5635510473.0667.73363
#Mann= 3 , 0 , 0
9163.112   0.045       09163.112   0.045       010473.06   0.045       0
#XS Ineff= 2 , 0
       09768.637                       0
Bank Sta=9163.112,10473.06
Exp/Cntr=0.3,0.1

Type RM Length L Ch R = 1 ,2179.661,195.311100,195.311100,195.311100
XS GIS Cut Line= 6
 1243669.7042121635654.822866246  1244177.148036635597.610098779
1244350.75021663635568.4069207911244449.65238151635564.540027067
1244660.50175813635575.2233517021245007.54470906 635528.56736289
#Sta/Elev= 30
9126.59745.171429179.40944.723029219.02841.692229242.13941.009129258.64841.53022
9285.06140.199779400.61738.111659440.23738.661379483.158  36.0359499.66637.45702
9522.77737.408279535.98435.670249592.111 34.74689721.92334.678849758.50536.07254
9778.35335.069149877.19136.382319896.87734.451169959.32834.333789998.79332.53966
10031.7232.3780810061.3632.56753 10071.233.9421410146.7537.0328410222.5942.42753
10255.6446.2232710315.58 50.167410361.66 56.254810368.2956.3587510474.0273.87937
#Mann= 3 , 0 , 0
9126.597  0.0707       09126.597  0.0707       010474.02  0.0707       0
#XS Ineff= 2 , 0
       09811.639                       0
Bank Sta=9126.597,10474.02
Exp/Cntr=0.3,0.1

Type RM Length L Ch R = 1 , 1984.35,195.311100,195.311100,195.311100
XS GIS Cut Line= 6
1243653.60483375635818.1165607271244384.13741985635785.392093018
1244561.23675737635758.1978086231244657.91700813635724.366366789
1244729.56523931635706.8292249141245079.62789848635656.174938366
#Sta/Elev= 30
9034.69441.563849086.92141.072129109.90939.339139172.30839.060499234.70635.53237
9264.26336.074359336.51435.03456 9389.0633.29898 9540.1331.567549553.26630.35663
9638.65332.234379753.59830.433349803.25532.111379819.85130.845459833.12832.03444
9879.59832.8678710004.8730.1204110010.8731.68147 10111.533.7798410128.2936.43748
10138.2736.6379310161.5639.4688910194.8244.9830310211.3849.7111710234.5752.03051
10251.1356.8190110300.8166.73064   1037786.1847810446.56102.148610475.54110.1998
#Mann= 3 , 0 , 0
9034.694  0.1053       09034.694  0.1053       010475.54  0.1053       0
#XS Ineff= 2 , 0
       09821.605                       0
Bank Sta=9034.694,10475.54
Exp/Cntr=0.3,0.1

Type RM Length L Ch R = 1 ,1789.039,195.311100,195.311100,195.311100
XS GIS Cut Line= 6
1243690.40341279635917.0127419081244428.09959096635929.868200958
1244581.32155728635918.4951487631244652.38214734635917.381676391
1244935.04372656635907.0420609561245077.50510782635899.116900384
#Sta/Elev= 30
9091.92538.528789140.117 38.9414 9172.9336.858499245.11935.158049363.24734.74609
9386.21732.366389441.99932.414619524.03228.58371 9543.7229.701319609.34728.40727
 9642.1629.298589688.09927.563779796.38330.157139865.38327.543419894.99229.16197
 9950.92 29.432910052.7228.2258610059.29 29.337910128.2330.8761610203.7435.80194
10226.7238.2793610246.4242.3879410325.2151.9525310358.0658.9787610374.4960.27593
10400.7869.25302 10420.572.8141210430.3575.88982 10466.572.7955410479.9876.62537
#Mann= 3 , 0 , 0
9091.925  0.0531       09091.925  0.0531       010479.98  0.0531       0
#XS Ineff= 2 , 0
       09914.334                       0
Bank Sta=9091.925,10479.98
Exp/Cntr=0.3,0.1

Type RM Length L Ch R = 1 ,1593.728,272.643600,272.643600,272.643600
XS GIS Cut Line= 6
1243743.30137014636013.6090118741244329.72035846636037.471985534
1244546.23738563636074.1537939461244696.50037098 636139.80701977
 1244832.5760963636174.1415032891245083.06187904636192.783204973
#Sta/Elev= 30
9120.44637.105419237.17835.430959256.87233.383769296.26135.068939329.08531.82981
9368.47330.469469417.70930.521359496.48627.029529552.28627.164349608.08725.64756
9740.05226.093439756.61424.864389796.36124.888169819.58725.799149862.926 25.1812
9896.29327.114519943.95127.999889954.32826.544939990.67227.057169997.98925.11872
10012.7726.5379210066.9224.7083210091.6124.8106310129.2427.5898310154.0226.04658
10240.4327.4831710253.7126.6782410395.55 35.426810454.6336.7711910483.4940.79036
#Mann= 3 , 0 , 0
9120.446  0.0941       09120.446  0.0941       010483.49  0.0941       0
#XS Ineff= 2 , 0
       09896.674        10087.92       0
Bank Sta=9120.446,10483.49
Exp/Cntr=0.3,0.1

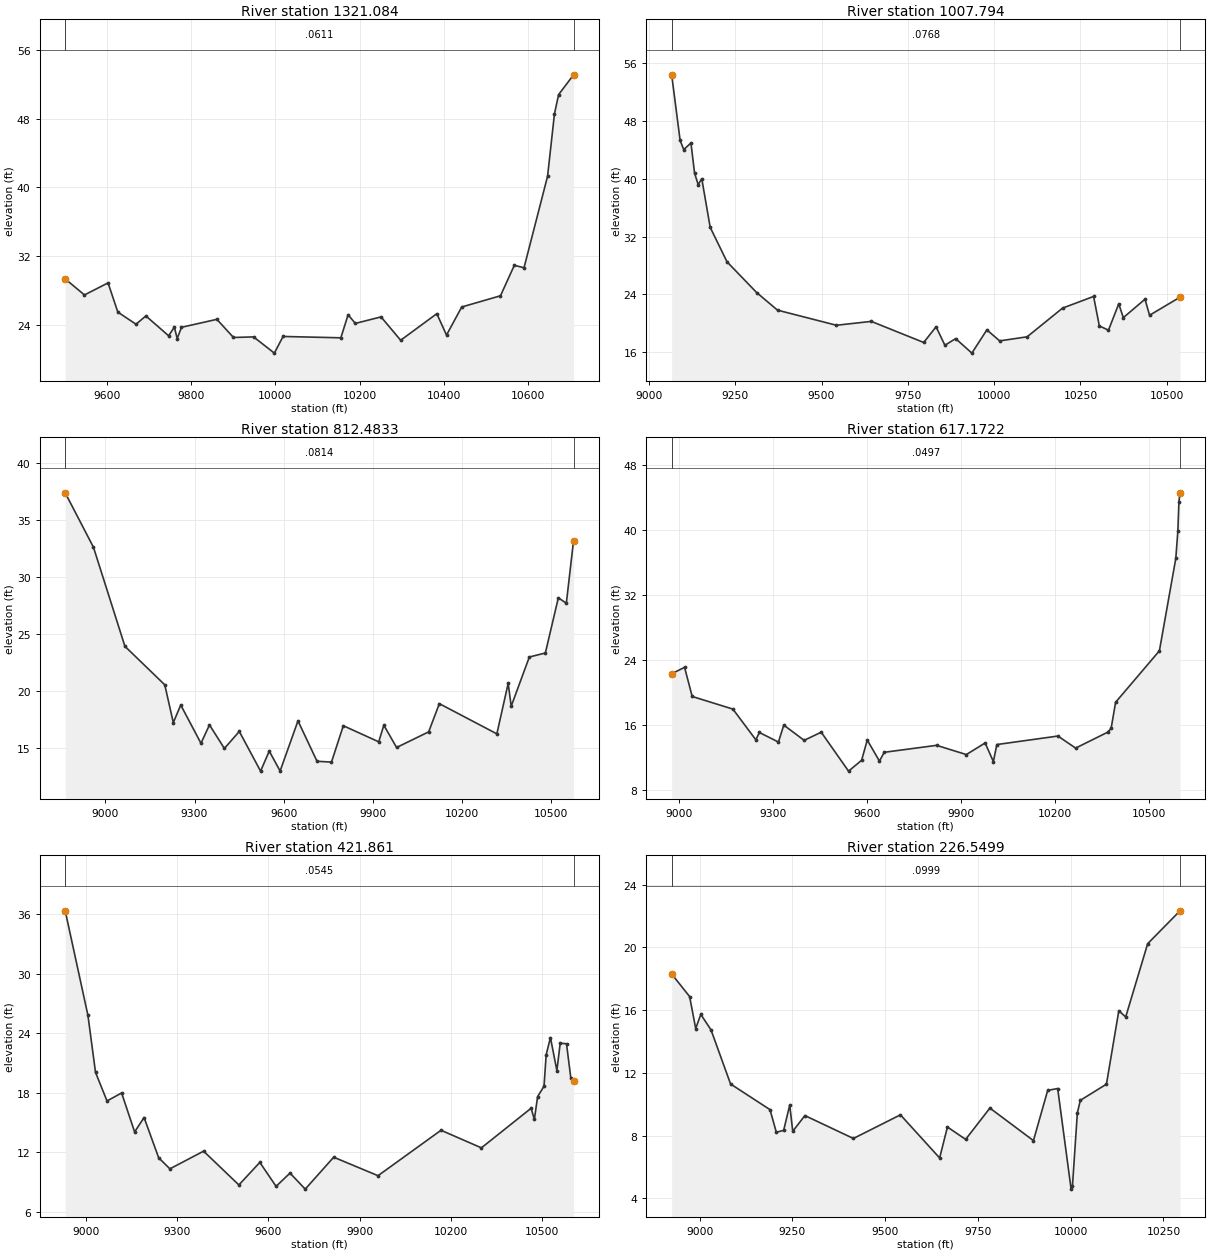
Type RM Length L Ch R = 1 ,1321.084,313.289800,313.289800,313.289800
XS GIS Cut Line= 6
1244007.98623663636212.1182446481244282.67610848636253.911801249
1244586.10247365636392.4561211171244725.08938447  636434.3664691
1244850.00170726636448.1579147881245171.54621902636436.792670786
#Sta/Elev= 30
9501.59429.334919547.24327.466169603.21828.871679626.37425.470649669.50624.05262
9692.88625.02053 9746.8522.708659760.41823.711049767.20222.385139777.37923.69342
9861.25624.624339900.70122.508719948.36622.576559997.58520.6852510018.2622.62842
10155.3122.4707710172.4925.1562410189.6424.14882 10250.624.9081510297.1622.18461
10382.88 25.281410405.8722.7879810441.9826.06368 10533.927.3695110566.7330.92389
10589.7130.6337310645.5241.2906510661.9348.5820110671.7850.8169710707.1353.12229
#Mann= 3 , 0 , 0
9501.594  0.0611       09501.594  0.0611       010707.13  0.0611       0
#XS Ineff= 2 , 0
       0 9863.86        10193.11       0
Bank Sta=9501.594,10707.13
Exp/Cntr=0.3,0.1

Type RM Length L Ch R = 1 ,1007.794,195.311100,195.311100,195.311100
XS GIS Cut Line= 6
1243577.70776448636974.9718892131244232.67634574636738.729638413
1244352.06694669636683.3443060371244542.38778052636569.280140147
1244670.93434611636538.9709409031244957.95083323 636501.55873993
#Sta/Elev= 30
9065.85554.387719090.357  45.3029100.80444.047439121.69844.953279132.14540.79133
9142.59239.196069153.03940.011699177.41533.283639226.16728.512189312.18124.25354
9372.42321.825179543.05619.735259644.04220.270839795.86417.352859831.692 19.5259
9857.25816.969949888.49317.886129935.36615.879379978.80719.0992810015.9217.57227
10095.4518.1375910198.0122.1069710287.9823.7221110304.56  19.64510331.0719.05117
10360.8322.7016810374.0520.7861610436.8723.3433510450.0921.1199110538.2423.61977
#Mann= 3 , 0 , 0
9065.855  0.0768       09065.855  0.0768       010538.24  0.0768       0
#XS Ineff= 2 , 0
       09777.489         10230.4       0
Bank Sta=9065.855,10538.24
Exp/Cntr=0.3,0.1

Type RM Length L Ch R = 1 ,812.4833,195.311100,195.311100,195.311100
XS GIS Cut Line= 6
1243566.20820856637294.6595445871244275.45235819636974.848693222
 1244481.1298061636848.0355433371244627.69626084636719.443367541
1244735.68882924 636655.32771498 1245090.9864974636555.379611924
#Sta/Elev= 30
8864.69737.374238959.78332.608189065.68423.931169199.81620.558799228.47617.24828
9253.55418.787259321.62315.440779350.28417.04729 9400.44 14.98529450.59616.47516
9522.247 12.99969551.42614.75452 9587.9713.007379648.11817.401339712.29813.86082
9760.92513.791849800.71816.976969919.87615.566249937.08817.019639980.00415.06941
10087.95 16.438810123.9118.9092510317.4816.2640610355.5720.6845310365.7518.68385
10426.8122.9946910480.7123.34635 10524.428.1821210551.2927.7032310575.5333.17789
#Mann= 3 , 0 , 0
8864.697  0.0814       08864.697  0.0814       010575.53  0.0814       0
#XS Ineff= 2 , 0
       09776.604        10150.54       0
Bank Sta=8864.697,10575.53
Exp/Cntr=0.3,0.1

Type RM Length L Ch R = 1 ,617.1722,195.311200,195.311200,195.311200
XS GIS Cut Line= 6
1243768.60039327637460.2531502541244591.33715716636978.881986544
1244664.95670652636938.2874822911244920.25779876636809.572270051
1245086.69866577636740.4023370591245201.80841637636701.057248488
#Sta/Elev= 30
8975.44222.359219016.66823.148159041.045 19.5654  9171.218.009939244.60414.23013
  9255.815.134449316.78413.955259333.89316.04258 9398.9714.167579453.546 15.1688
9540.92210.37857 9582.7111.713619600.70914.202189639.74311.611339654.96512.69468
9822.40913.551829917.54812.415879977.58213.8443510003.8911.55534 10015.113.64977
10210.3914.6951810266.9213.2118210369.6815.1728310380.4315.6429410394.7618.85294
10534.7525.1836110587.1736.5533610593.6939.8870610597.1643.5268910600.5944.62092
#Mann= 3 , 0 , 0
8975.442  0.0497       08975.442  0.0497       010600.59  0.0497       0
#XS Ineff= 2 , 0
       09826.446        10167.31       0
Bank Sta=8975.442,10600.59
Exp/Cntr=0.3,0.1

Type RM Length L Ch R = 1 , 421.861,195.311100,195.311100,195.311100
XS GIS Cut Line= 6
1243832.99790654637630.4465782791244394.31346795637340.239975989
1244511.35889873 637270.486895741244972.10630128636973.306631863
1245105.22741455636905.1149065791245295.55686396636827.334915385
#Sta/Elev= 30
8931.94436.348689006.638 25.80269031.64120.045259069.42517.159829117.43917.96526
9160.22814.033429191.30715.489499239.32111.426919276.25510.307629387.056 12.0937
9503.1268.6828699571.99410.959659625.4638.5414799671.2949.8809339721.3128.261248
9814.91211.483729960.7439.617462 10167.914.2030610300.66  12.42710464.1416.42226
10474.8915.2997810485.5417.5974710506.6618.64657 10513.721.8203410527.7923.54755
10548.9120.2317710559.9622.9926210580.59 22.931110594.6719.50553 10603.719.20205
#Mann= 3 , 0 , 0
8931.944  0.0545       08931.944  0.0545       0 10603.7  0.0545       0
#XS Ineff= 2 , 0
       09861.602        10157.91       0
Bank Sta=8931.944,10603.7
Exp/Cntr=0.3,0.1

Type RM Length L Ch R = 1 ,226.5499,195.311100,195.311100,195.311100
XS GIS Cut Line= 6
1244014.69089055637874.2371644081244731.25188741637341.940281361
 1244864.9808543637260.3966225391244915.49043655637239.334183678
1245070.24914864637158.0160240681245152.51118252637118.753164649
#Sta/Elev= 30
8924.60318.310288973.00816.867818989.35614.830529003.078 15.73089030.58714.74473
9083.35711.290849189.6199.6536899206.6448.2109729226.4038.3330829242.7519.945338
9250.9258.2741369283.6219.2757929414.4057.8142789541.102 9.322799646.7886.570937
9667.7998.5460559716.8447.7563959782.236 9.753869899.6087.6774749938.03510.88353
9964.93411.0011410001.144.582152 10004.74.76925410017.949.44683310026.0410.24924
10096.35 11.2791 10129.715.9637410148.2415.5688110207.4620.2431210294.58 22.3399
#Mann= 3 , 0 , 0
8924.603  0.0999       08924.603  0.0999       010294.58  0.0999       0
#XS Ineff= 2 , 0
       09888.935        10130.78       0
Bank Sta=8924.603,10294.58
Exp/Cntr=0.3,0.1

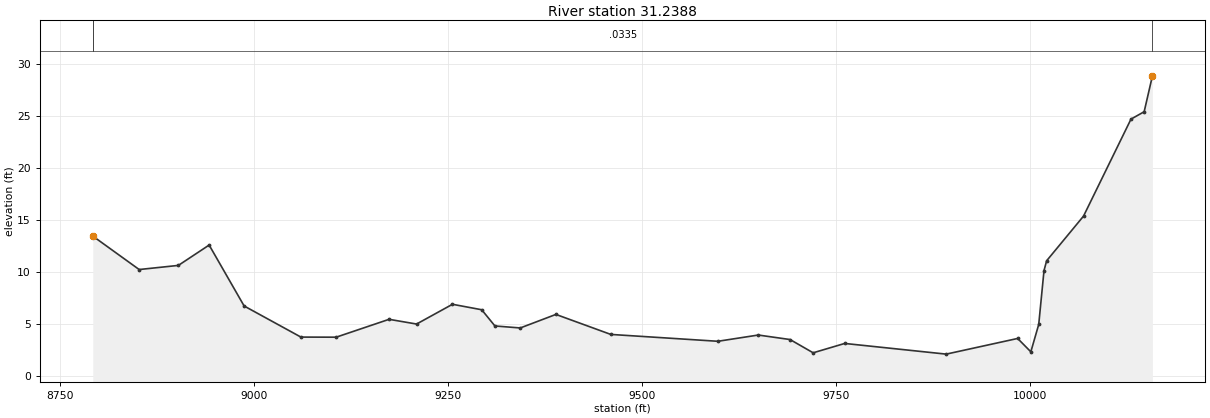
Type RM Length L Ch R = 1 , 31.2388,0.000000,0.000000,0.000000
XS GIS Cut Line= 6
1244049.18955842 638210.024198131244219.38298646638088.128905073
1244465.47348374637791.440361574 1244725.3634482 637556.84942022
1244909.35634339637444.1537719221245107.14870569637391.255814552
#Sta/Elev= 30
8792.57713.452648852.36810.231748902.86110.62892 8942.5212.589658987.6076.720971
9060.7783.7256799106.1723.7150859174.3735.4362989209.8084.9815599256.0596.884526
9293.725 6.358559310.7754.7962989343.4214.6048139389.3525.9086119460.0683.982096
9598.0633.3211769650.1173.9233599691.0943.4887759720.833 2.211579761.464 3.11253
9892.2732.0841599984.3293.59309510001.312.307402 10011.54.94774310018.29 10.1306
10021.6911.0774710069.2315.3785210130.3624.7177910147.3425.42987   1015828.88789
#Mann= 3 , 0 , 0
8792.577  0.0335       08792.577  0.0335       0   10158  0.0335       0
#XS Ineff= 2 , 0
       09931.038                       0
Bank Sta=8792.577,10158
Exp/Cntr=0.3,0.1